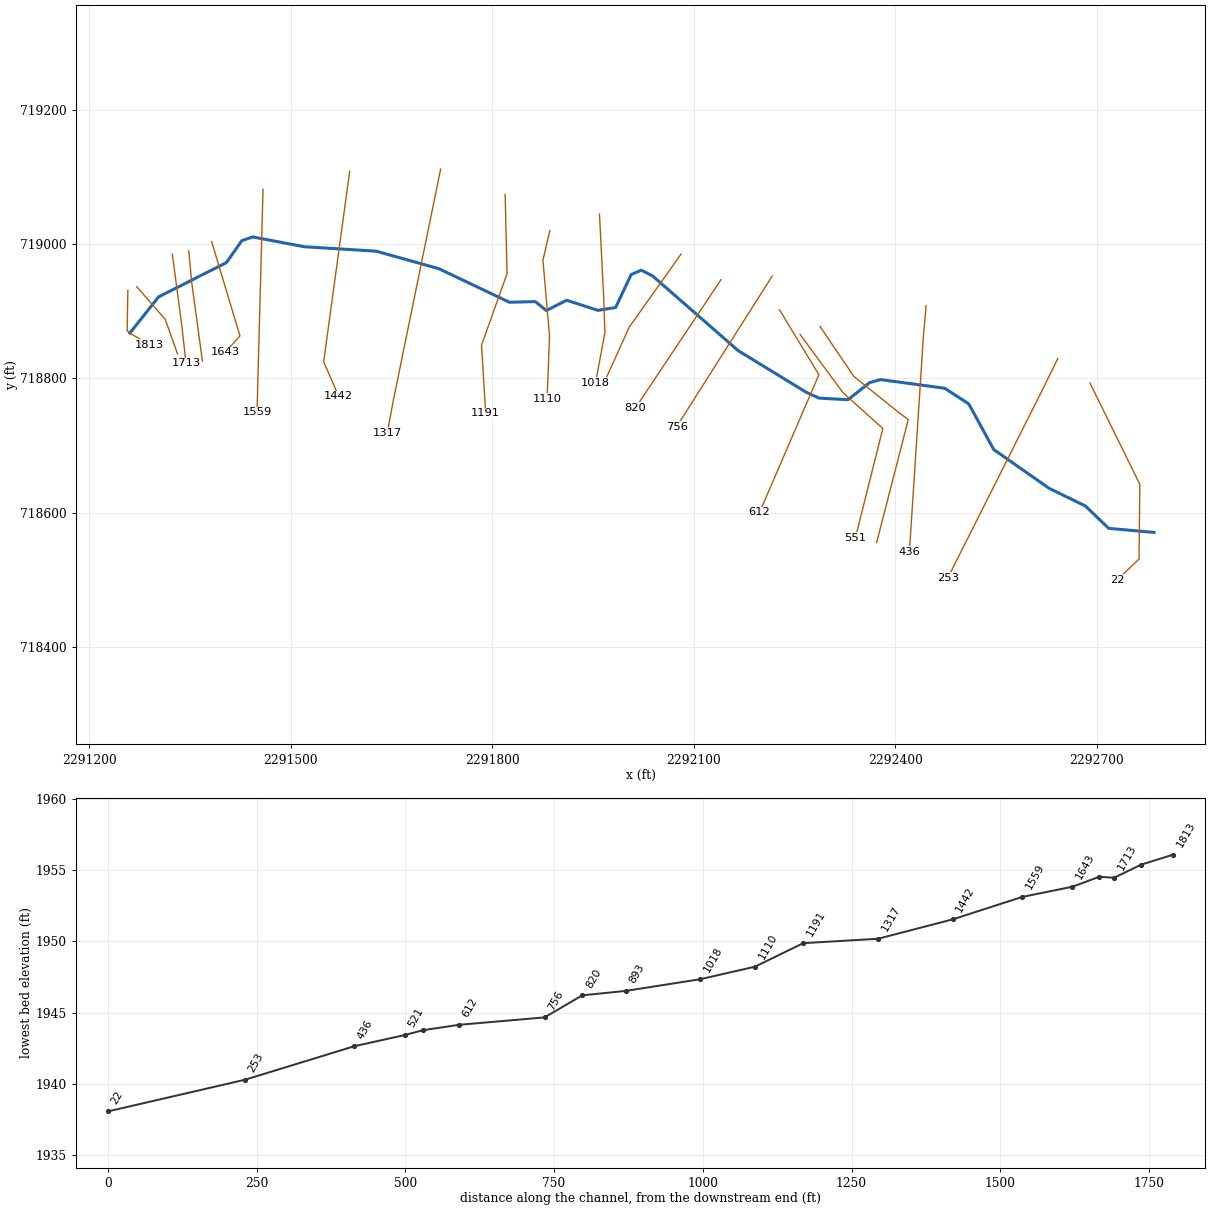
--- CLYLCKRNT2.prj (project) ---

Proj Title=CLYLCKRNT2
Current Plan=p01
Default Exp/Contr=0,0
English Units
Geom File=g01
Flow File=f01
Plan File=p01
BEGIN DESCRIPTION:
----------MODEL BY WOOD PLC 2022----------
AFH study
Randolph County, WV
HEC-RAS Version: RAS 6.2
Vertical Datum: NAVD88
Projection: NAD 1983 StatePlane West Virginia S FIPS 4702 (US Feet)
Terrain: 1-meter LIDAR (FEMA Region III 3DEP collected 2016-2018)
Land Use: 2019 NLCD
Hydrologic Method:
WV SIR2010-5033 regression equations
Additional Model Notes:
None
END DESCRIPTION:
DSS Export Rating Curves= 0
DSS Export Rating Curve Sorted= 0
DSS Export Volume Flow Curves= 0
DXF OffsetX= 0
DXF OffsetY= 0
DXF ScaleX= 0
DXF ScaleY= 0

--- CLYLCKRNT2.p01 (plan) ---

Plan Title=Floodplain
Program Version=6.20
Short Identifier=Floodplain
Geom File=g01
Flow File=f01
Subcritical Flow
K Sum by GR= 0
Std Step Tol= 0.01
Critical Tol= 0.01
Num of Std Step Trials= 20
Max Error Tol= 0.3
Flow Tol Ratio= 0.001
Split Flow NTrial= 30
Split Flow Tol= 0.02
Split Flow Ratio= 0.02
Log Output Level= 0
Friction Slope Method= 1
Unsteady Friction Slope Method= 2
Unsteady Bridges Friction Slope Method= 1
Parabolic Critical Depth
Global Vel Dist= 0 , 0 , 0
Global Log Level= 0
CheckData=True
Encroach Param=-1 ,0,0, 0
Mapping Interval=1HOUR
Computation Time Step Use Courant=        0
Computation Time Step Use Time Series=    0
Computation Time Step Count To Double=0
Computation Time Step Max Doubling=0
Computation Time Step Max Halving=0
Computation Time Step Residence Courant=0
Run HTab= 0
Run UNet= 0
Run Sediment= 0
Run PostProcess= 0
Run WQNet= 0
Run RASMapper=-1
UNET Theta= 0
UNET Theta Warmup= 0
UNET ZTol= 0
UNET ZSATol= 0
UNET MxIter= 0
UNET Max Iter WO Improvement= 0
UNET MaxInSteps= 0
UNET DtIC= 0
UNET DtMin= 0
UNET MaxCRTS= 0
UNET WFStab= 0
UNET SFStab= 0
UNET WFX= 1
UNET SFX= 1
UNET Gravity=32.174
UNET 1D Methodology=Finite Difference
UNET DSS MLevel= 1
UNET Pardiso=0
UNET DZMax Abort= 0
UNET Use Existing IB Tables= 0
UNET Froude Reduction=False
UNET Froude Limit= 0
UNET Froude Power= 0
UNET D1 Cores= 0
UNET WindReference=Eulerian
UNET WindDragFormulation=Hsu (1988)
UNET D2 Coriolis=0
UNET D2 Cores= 0
UNET D2 Theta= 1
UNET D2 Theta Warmup= 1
UNET D2 Z Tol= 0.01
UNET D2 Volume Tol= 0.01
UNET D2 Max Iterations= 20
UNET D2 Equation= 0
UNET D2 RampUpFraction=0.1
UNET D2 TimeSlices= 1
UNET D2 Turbulence Formulation=Non-Conservative (original)
UNET D2 Eddy Viscosity=0.3
UNET D2 Transverse Eddy Viscosity=0.1
UNET D2 Smagorinsky Mixing=0
UNET D2 BCVolumeCheck=0
UNET D2 Cores=0
UNET D2 SolverType=PARDISO (Direct)
UNET D2 Minimum Iterations= 2147483647
UNET D2 Maximum Iterations= 2147483647
UNET D2 Restart Number= 10
UNET D2 Relaxation Coeff=1.3
UNET D2 SOR Precondition Iterations= 10
UNET D2 ILUT Maximum Fill= 8
UNET D2 ILUT Tolerance=1E-08
UNET D1D2 MaxIter= 0
UNET D1D2 ZTol=0.01
UNET D1D2 QTol=0.1
UNET D1D2 MinQTol=1
Write IC File= 0
Write IC File at Fixed DateTime=0
Write IC File at Sim End=0
Echo Input=False
Echo Parameters=False
Echo Output=False
Write Detailed= 0
HDF Write Warmup=0
HDF Write Time Slices=0
HDF Flush=0
HDF Compression= 1
HDF Chunk Size= 1
HDF Spatial Parts= 1
HDF Use Max Rows=0
HDF Fixed Rows= 1
Calibration Method= 0
Calibration Iterations= 20
Calibration Max Change=0.05
Calibration Tolerance=0.2
Calibration Maximum=1.5
Calibration Minimum=0.5
Calibration Optimization Method= 1
WQ AD Non Conservative
WQ ULTIMATE=-1
WQ Max Comp Step=1HOUR
WQ Output Interval=15MIN
WQ Output Selected Increments= 0
WQ Output face flow=0
WQ Output face velocity=0
WQ Output face area=0
WQ Output face dispersion=0
WQ Output cell volume=0
WQ Output cell surface area=0
WQ Output cell continuity=0
WQ Output cumulative cell continuity=0
WQ Output face conc=0
WQ Output face dconc_dx=0
WQ Output face courant=0
WQ Output face peclet=0
WQ Output face adv mass=0
WQ Output face disp mass=0
WQ Output cell mass=0
WQ Output cell source sink temp=0
WQ Output nsm pathways=0
WQ Output nsm derived pathways=0
WQ Create Restart=0
WQ Fixed Restart=0
WQ System Summary=0
WQ Write To DSS=0
Sorting and Armoring Iterations= 10
XS Update Threshold= 0.02
Bed Roughness Predictor= 0
Hydraulics Update Threshold= 0.02
Energy Slope Method= 1
Volume Change Method= 1
Sediment Retention Method= 0
Sediment TS Multiplier= 1
Warm Up Method= 0
XS Weighting Method= 0
Number of US Weighted Cross Sections= 1
Number of DS Weighted Cross Sections= 1
Upstream XS Weight=0
Main XS Weight=1
Downstream XS Weight=0
Number of DS XS's Weighted with US Boundary= 1
Upstream Boundary Weight= 1
Weight of XSs Associated with US Boundary= 0
Number of US XS's Weighted with DS Boundary= 1
Downstream Boundary Weight= 0.5
Weight of XSs Associated with DS Boundary= 0.5
Percentile Method= 0
Sediment Output Level= 3
Mass or Volume Output= 0
Output Increment Type= 1
Profile and TS Output Increment= 1
Transport Output Increment 1
XS Output Flag= 0
XS Output Increment= 10
Read HDF5 Sediment Hotstart= 0
Sediment Hotstart Type= 0
Write Gradation File= 0
Read Gradation Hotstart= 0
Write HDF5 File= 1
Write Binary Output= 1
Write DSS Sediment File= 0
DSS Sediment Output Type= 1
SV Curve= 0
Specific Gage Flag= 0
Subcell Erosion Methods= 0
Subcell Deposition Methods= 0
Advection Scheme= 1
Matrix Solver= 0
Implicit Weighting Factor= 1
Maximum Outer Loop Convergence Iterations= 5
Convergence Maximum Absolute= 0.001
Convergence RMSE= 0.0001
Grain Fractions Max Abs Error= 0.001
Max Subgrid Regions= 1
Max Subgrid Length Scale= 3.402823E+38
Initial Layer Thickness= 3.402823E+38
Min Layer Thickness= 3.402823E+38
Max Layer Thickness= 3.402823E+38
Number of Layers= 5

--- CLYLCKRNT2.f01 (steady flow) ---

Flow Title=Flow
Program Version=6.30
Number of Profiles= 1
Profile Names=P100yr
River Rch & RM=CLYLCKRNT2,Main,1813
     337
Boundary for River Rch & Prof#=CLYLCKRNT2,Main            , 1
Up Type= 0
Dn Type= 3
Dn Slope=0.01105
DSS Import GetInterval= 0
DSS Import GetPeak= 0
DSS Import FillOption= 0

--- CLYLCKRNT2.g01 (geometry) ---

Geom Title=Geometry
Program Version=6.20

River Reach=CLYLCKRNT2      ,Main
Reach XY= 30
     2291260.239      718867.412     2291302.947      718921.231
     2291403.989      718972.273     2291426.906      719004.912
     2291443.225      719010.468     2291519.961      718995.884
     2291626.906      718989.287     2291720.309      718963.245
     2291825.366      718913.2682291864.07118333718914.201581117
2291880.29239335718900.8905983772291910.68442599718916.218897756
     2291957.148      718901.211     2291983.537      718905.377
     2292006.758      718954.563     2292021.731      718960.933
     2292038.398      718952.599     2292166.176      718841.141
 2292267.5811394718779.1199633382292286.62989979718770.488493785
2292329.61827376718768.124815594     2292361.903      718793.562
     2292377.981      718798.085     2292473.467      718785.238
     2292509.511      718761.871     2292546.607      718694.011
     2292629.023       718636.28     2292683.189      718609.891
     2292717.912      718576.558     2292785.453      718570.555

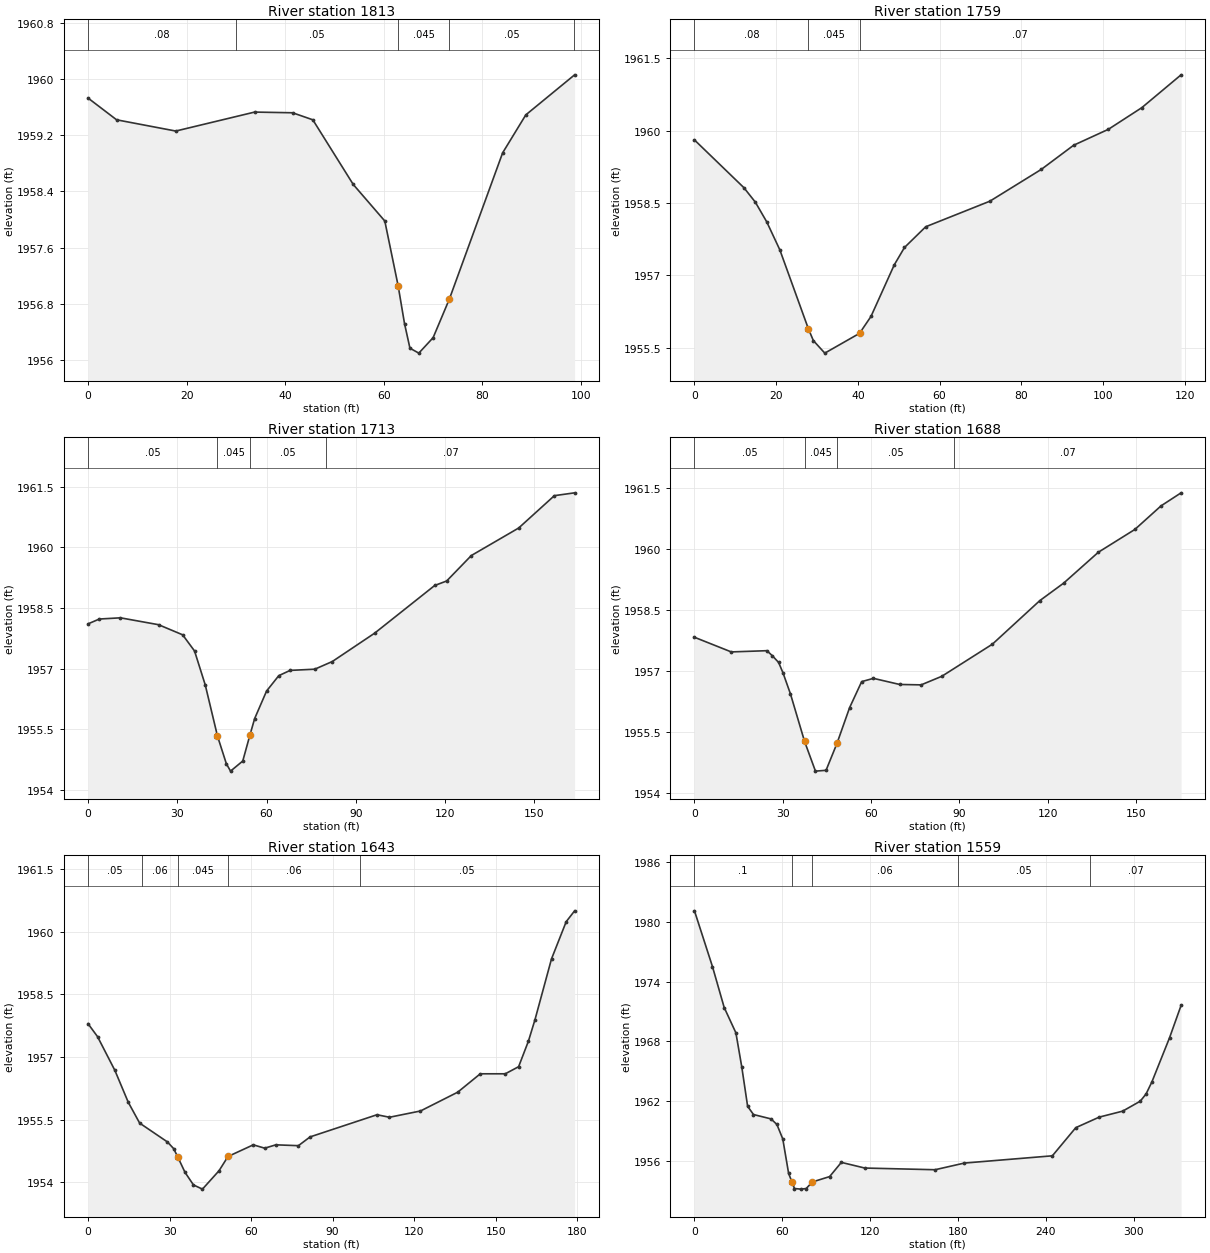
Type RM Length L Ch R = 1 ,1813    ,55.7,54.3,52.5
XS GIS Cut Line= 5
2291257.19930789718930.9698693522291256.12708302718870.752571435
2291264.66563762718864.4726022432291277.07403303718857.447829479
2291288.44486843718850.028960699
#Sta/Elev= 17
       0 1959.73     5.8 1959.42    17.8 1959.26    33.8 1959.53    41.5 1959.52
    45.6 1959.42    53.8  1958.5    60.2 1957.98    62.9 1957.06    64.2 1956.52
    65.3 1956.17    67.1  1956.1      70 1956.32    73.3 1956.87    84.1 1958.95
    88.8 1959.49    98.7 1960.06
#Mann= 5 ,-1,0
       0     .08       0      30     .05       0    62.9    .045       0
    73.3     .05       0   98.66     .07       0
Bank Sta=62.9,73.3
XS Rating Curve= 0 ,0
Exp/Cntr(USF)=0,0
Exp/Cntr=0.3,0.1

Type RM Length L Ch R = 1 ,1759    ,48.4,45.6,42
XS GIS Cut Line= 3
 2291270.4326396718936.4516653742291312.91419642 718887.65053811
 2291331.1122187 718836.39180012
#Sta/Elev= 19
       0 1959.81    12.1 1958.82    14.9 1958.52    17.7 1958.11    20.9 1957.53
    27.9 1955.89    29.1 1955.65    31.9 1955.39    40.4  1955.8    43.2 1956.15
    48.9 1957.22    51.4 1957.58    56.6 1958.01    72.3 1958.54    84.9  1959.2
    92.8  1959.7   101.3 1960.03   109.5 1960.48   119.1 1961.16
#Mann= 3 ,-1,0
       0     .08       0    27.9    .045       0    40.4     .07       0
Bank Sta=27.9,40.4
XS Rating Curve= 0 ,0
Exp/Cntr(USF)=0,0
Exp/Cntr=0.3,0.1

Type RM Length L Ch R = 1 ,1713    ,24.7,24.8,24.3
XS GIS Cut Line= 3
2291323.40770793718984.6754441962291337.45407996718879.554208354
2291343.79760282718822.462502682
#Sta/Elev= 25
       0 1958.11     3.8 1958.23    10.9 1958.26    23.7 1958.09    31.8 1957.84
    35.8 1957.44    39.4  1956.6    43.51955.338    46.5 1954.65    47.9 1954.47
      52 1954.72    54.4 1955.36      56 1955.77      60 1956.45    64.1 1956.83
    67.9 1956.96    76.2 1956.99    82.1 1957.18    96.3 1957.88   116.5 1959.06
   120.5 1959.17   128.8  1959.8   144.7 1960.48   156.7 1961.28   163.5 1961.35
#Mann= 4 ,-1,0
       0     .05       0    43.5    .045       0    54.4     .05       0
      80     .07       0
Bank Sta=43.5,54.4
XS Rating Curve= 0 ,0
Exp/Cntr(USF)=0,0
Exp/Cntr=0.3,0.1

Type RM Length L Ch R = 1 ,1688    ,44.6,45.1,46.2
XS GIS Cut Line= 3
2291347.87558179718989.6596407232291352.40666954718941.630110554
2291368.26547668718825.634264108
#Sta/Elev= 24
       0 1957.83    12.5 1957.47    24.6  1957.5    26.4 1957.38    28.6 1957.21
    30.1 1956.95    32.6 1956.44    37.4 1955.27    41.1 1954.54    44.7 1954.56
    48.4 1955.22    52.7  1956.1    56.8 1956.74    60.8 1956.82    69.7 1956.67
      77 1956.66      84 1956.87   101.2 1957.66   117.3 1958.73   125.4 1959.16
   137.2 1959.92   149.6 1960.48   158.5 1961.06   165.3 1961.38
#Mann= 4 ,-1,0
       0     .05       0    37.4    .045       0    48.4     .05       0
   88.24     .07       0
Bank Sta=37.4,48.4
XS Rating Curve= 0 ,0
Exp/Cntr(USF)=0,0
Exp/Cntr=0.3,0.1

Type RM Length L Ch R = 1 ,1643    ,84.5,84,81.3
XS GIS Cut Line= 3
2291382.01322802719003.388670728 2291424.1473478718863.108977196
2291402.44339546718838.848395453
#Sta/Elev= 30
       0  1957.8     3.5 1957.49     9.9 1956.68    14.8 1955.92      19 1955.42
    29.2 1954.97    31.5 1954.81   32.94 1954.62    35.7 1954.24    38.8 1953.94
    42.1 1953.84    48.2 1954.28    51.51954.621    60.8  1954.9      65 1954.82
    69.1  1954.9    77.4 1954.88    81.7 1955.09   106.3 1955.62   110.9 1955.56
   122.3 1955.71     136 1956.16   144.3  1956.6   153.5  1956.6   158.4 1956.77
     162 1957.38   164.4 1957.89   170.5 1959.35   175.9 1960.24     179  1960.5
#Mann= 5 ,-1,0
       0     .05       0      20     .06       0   32.94    .045       0
    51.5     .06       0     100     .05       0
Bank Sta=32.94,51.5
XS Rating Curve= 0 ,0
Exp/Cntr(USF)=0,0
Exp/Cntr=0.3,0.1

Type RM Length L Ch R = 1 ,1559    ,117.8,117.3,116.2
XS GIS Cut Line= 2
2291458.50781362719081.4405105682291449.52989246718749.257427403
#Sta/Elev= 30
       0 1981.11    12.3  1975.5    20.3 1971.39    28.3 1968.84    32.3 1965.42
    36.3 1961.46    40.3 1960.63    52.3 1960.19    56.3 1959.63    60.3 1958.18
    64.3 1954.71   66.61 1953.83    68.3 1953.19    72.7 1953.13    76.3 1953.19
    80.5 1953.85    92.3 1954.39   100.3 1955.82   116.3 1955.25   164.3 1955.08
   184.3 1955.75   244.4 1956.48   260.4 1959.31   276.4 1960.37   292.4 1960.97
   304.4 1961.97   308.4  1962.7   312.4 1963.92   324.4 1968.34   332.3  1971.6
#Mann= 5 ,-1,0
       0      .1       0   66.61    .045       0    80.5     .06       0
     180     .05       0     270     .07       0
Bank Sta=66.61,80.5
XS Rating Curve= 0 ,0
Exp/Cntr(USF)=0,0
Exp/Cntr=0.3,0.1

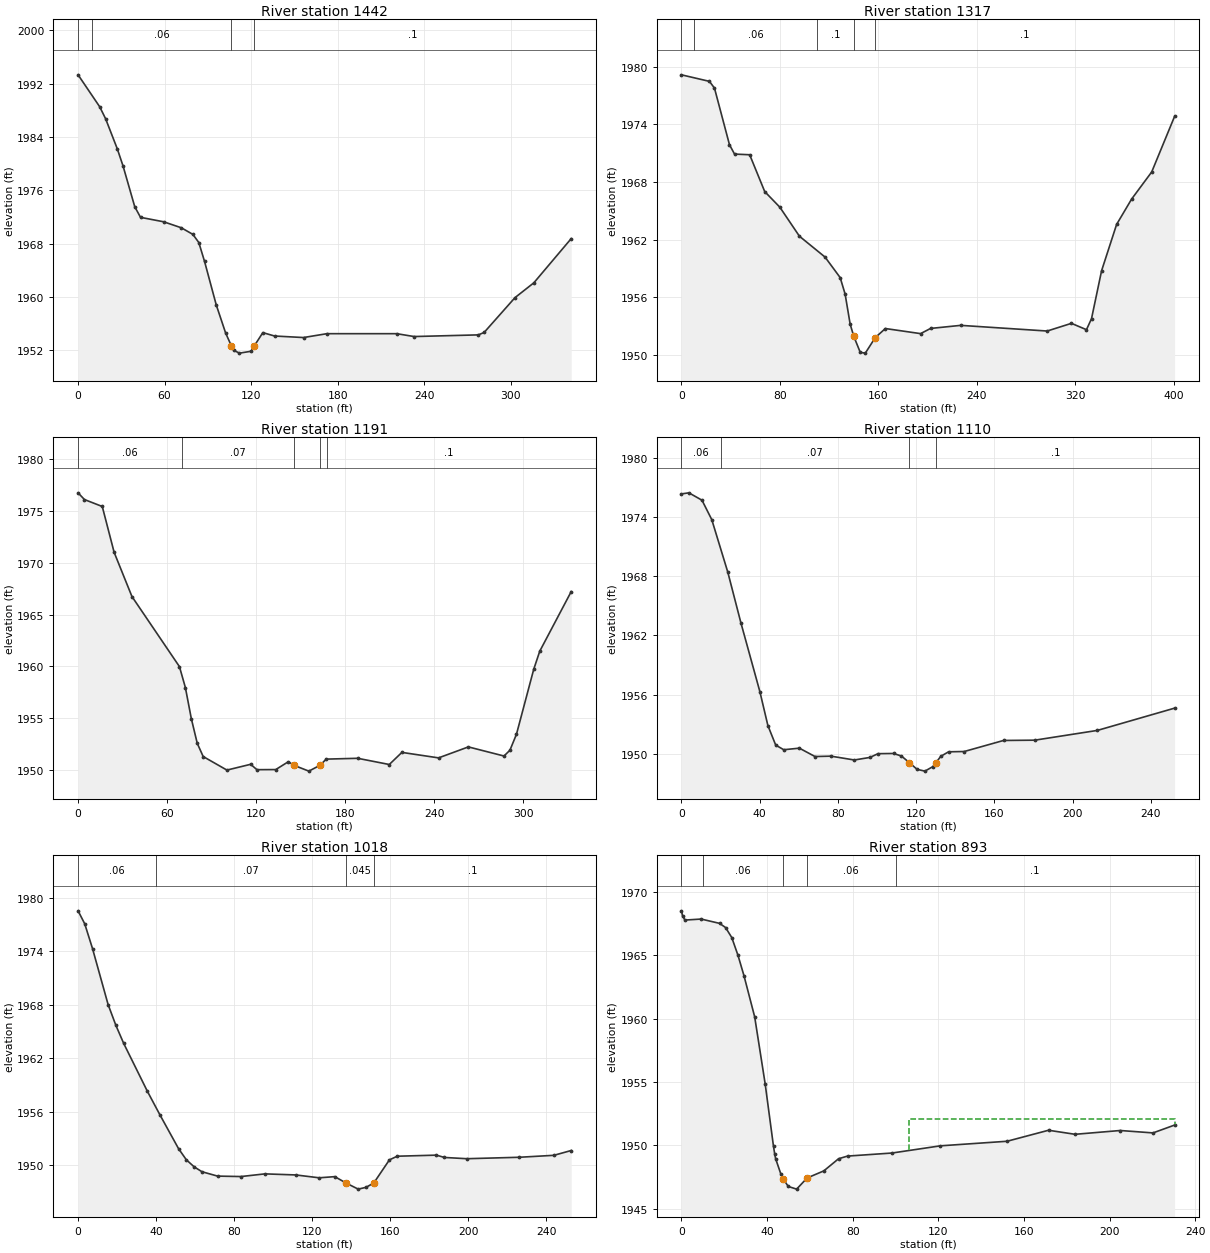
Type RM Length L Ch R = 1 ,1442    ,125.9,125.3,124.9
XS GIS Cut Line= 3
2291587.52363592719108.0804821232291548.83203626718824.665375426
2291571.18016267718773.421057719
#Sta/Elev= 30
       0 1993.34      15 1988.54    19.1 1986.74    27.2 1982.22    31.2 1979.64
    39.3 1973.53    43.3 1971.94    59.4 1971.27    71.6 1970.37    79.6 1969.38
    83.7 1968.16    87.7 1965.31    95.8 1958.79   102.3 1954.57   106.21952.682
   107.9 1951.97   111.9 1951.55     120 1951.83  122.27 1952.67   128.1 1954.63
   136.2 1954.12   156.3 1953.89   172.5 1954.47   220.9 1954.47     233 1954.04
   277.5 1954.29   281.5 1954.65   302.9 1959.88     316 1962.11   341.9 1968.75
#Mann= 4 ,-1,0
       0      .1       0      10     .06       0   106.2    .045       0
  122.27      .1       0
Bank Sta=106.2,122.27
XS Rating Curve= 0 ,0
Exp/Cntr(USF)=0,0
Exp/Cntr=0.3,0.1

Type RM Length L Ch R = 1 ,1317    ,126.2,125.8,123.7
XS GIS Cut Line= 3
2291722.98866511719111.4205341082291652.56903269718767.213269737
2291643.54301513718718.838976548
#Sta/Elev= 30
       0 1979.16    22.7 1978.48    26.8 1977.78      39 1971.88    43.1 1970.91
    55.4 1970.84    67.6 1967.01    79.9 1965.38    95.8 1962.36   116.6 1960.19
   128.9 1958.05   132.9 1956.34     137 1953.21   139.9 1951.95   145.2 1950.27
   149.3 1950.19   157.4 1951.81   165.6 1952.75   194.2 1952.22   202.3 1952.76
   226.8 1953.08     297 1952.49   316.7 1953.29   328.9 1952.63     333 1953.77
   341.2 1958.77   353.4 1963.59   365.6 1966.23   381.9 1969.05   400.5 1974.84
#Mann= 5 ,-1,0
       0      .1       0      10     .06       0     110      .1       0
   139.9    .045       0   157.4      .1       0
Bank Sta=139.9,157.4
XS Rating Curve= 0 ,0
Exp/Cntr(USF)=0,0
Exp/Cntr=0.3,0.1

Type RM Length L Ch R = 1 ,1191    ,77.2,81,82.4
XS GIS Cut Line= 4
2291819.06438385719073.470439715  2291821.877627 718955.80257891
2291783.89411437718849.4487435522291790.10959826718747.929173436
#Sta/Elev= 30
       0 1976.77     4.3 1976.12    16.3 1975.45    24.3 1971.02    36.3 1966.75
    68.3 1959.98    72.3 1957.96    76.3 1954.96    80.3 1952.57    84.3 1951.29
   100.3 1949.98   116.3 1950.54   120.5 1950.02   133.2 1950.03   141.7 1950.79
  145.421950.445   155.5 1949.88     163 1950.44   167.2 1951.04   188.4 1951.12
   209.7 1950.52   218.2 1951.69   242.9 1951.16     263 1952.22     287 1951.34
     291  1951.9   295.4 1953.44     307  1959.7   311.1 1961.47   332.3 1967.23
#Mann= 5 ,-1,0
       0     .06       0      70     .07       0  145.42    .045       0
     163     .07       0   167.7      .1       0
Bank Sta=145.42,163
XS Rating Curve= 0 ,0
Exp/Cntr(USF)=0,0
Exp/Cntr=0.3,0.1

Type RM Length L Ch R = 1 ,1110    ,91.7,92.1,90.5
XS GIS Cut Line= 4
2291885.70526448719020.2236366222291875.37062221718976.063347619
2291885.17160749718862.0918901822291881.51203599718769.712739937
#Sta/Elev= 30
       0 1976.35     3.8 1976.46    10.5 1975.71    15.5 1973.74    23.7 1968.41
    30.4 1963.27    40.1 1956.29    44.2 1952.85    48.2 1950.87    52.3  1950.4
    60.3 1950.56    68.3 1949.71    76.4 1949.75    88.4 1949.36    96.4 1949.62
   100.5    1950   108.5 1950.02   112.5 1949.76   116.5  1949.1   120.5 1948.41
   124.5 1948.23   128.5 1948.68   130.2  1949.1   132.6 1949.73   136.6 1950.19
   144.6 1950.22   164.7 1951.34   180.7 1951.37   212.7 1952.36   252.2 1954.62
#Mann= 4 ,-1,0
       0     .06       0      20     .07       0   116.5    .045       0
   130.2      .1       0
Bank Sta=116.5,130.2
XS Rating Curve= 0 ,0
Exp/Cntr(USF)=0,0
Exp/Cntr=0.3,0.1

Type RM Length L Ch R = 1 ,1018    ,126.9,125.1,121.1
XS GIS Cut Line= 4
2291959.54293466719044.5979132332291965.61723638718924.757726292
2291967.62617145718867.7187916332291953.64133271718793.319449535
#Sta/Elev= 30
       0 1978.55     3.4  1977.1     7.4 1974.32    15.4 1968.04    19.4  1965.7
    23.4 1963.68    35.5 1958.33      42 1955.66    51.5 1951.89    55.5 1950.64
    59.5 1949.85    63.5  1949.3    71.5 1948.81    83.5 1948.76    95.8 1949.06
   111.6 1948.94   123.6 1948.62   131.6 1948.75   137.5 1948.02   143.6 1947.35
   147.6 1947.55   151.6 1948.04   159.6 1950.63   163.6 1951.04   183.7 1951.16
   187.8  1950.9   199.3 1950.76     226 1950.92   243.9 1951.14   252.8 1951.68
#Mann= 4 ,-1,0
       0     .06       0      40     .07       0   137.5    .045       0
   151.6      .1       0
Bank Sta=137.5,151.6
XS Rating Curve= 0 ,0
Exp/Cntr(USF)=0,0
Exp/Cntr=0.3,0.1

Type RM Length L Ch R = 1 ,893     ,72.6,73,73
XS GIS Cut Line= 3
2292081.08655516718985.0325780982292003.83150899  718876.1958503
2291963.91262589 718787.83963914
#Sta/Elev= 30
       0 1968.51      .5 1968.12     1.6 1967.78     9.2 1967.86    17.8 1967.52
    20.6 1967.19    23.5  1966.4    26.4    1965    29.2 1963.39    34.2 1960.14
    39.1 1954.85      43  1949.9    43.6 1949.27      44 1948.93    46.5 1947.69
    47.61947.323    49.9 1946.74    53.8 1946.53    58.7 1947.41    66.5 1947.97
    73.4 1948.93    77.6 1949.14    98.3 1949.38     121 1949.95   152.1 1950.31
   171.5 1951.18   183.9 1950.86     205 1951.16   220.3 1950.97   230.4 1951.59
#Mann= 5 ,-1,0
       0     .07       0      10     .06       0    47.6    .045       0
    58.7     .06       0     100      .1       0
#XS Ineff= 2 , 0
                           106.4         1952.05
Permanent Ineff=
       F       F
Bank Sta=47.6,58.7
XS Rating Curve= 0 ,0
Exp/Cntr(USF)=0,0
Exp/Cntr=0.3,0.1

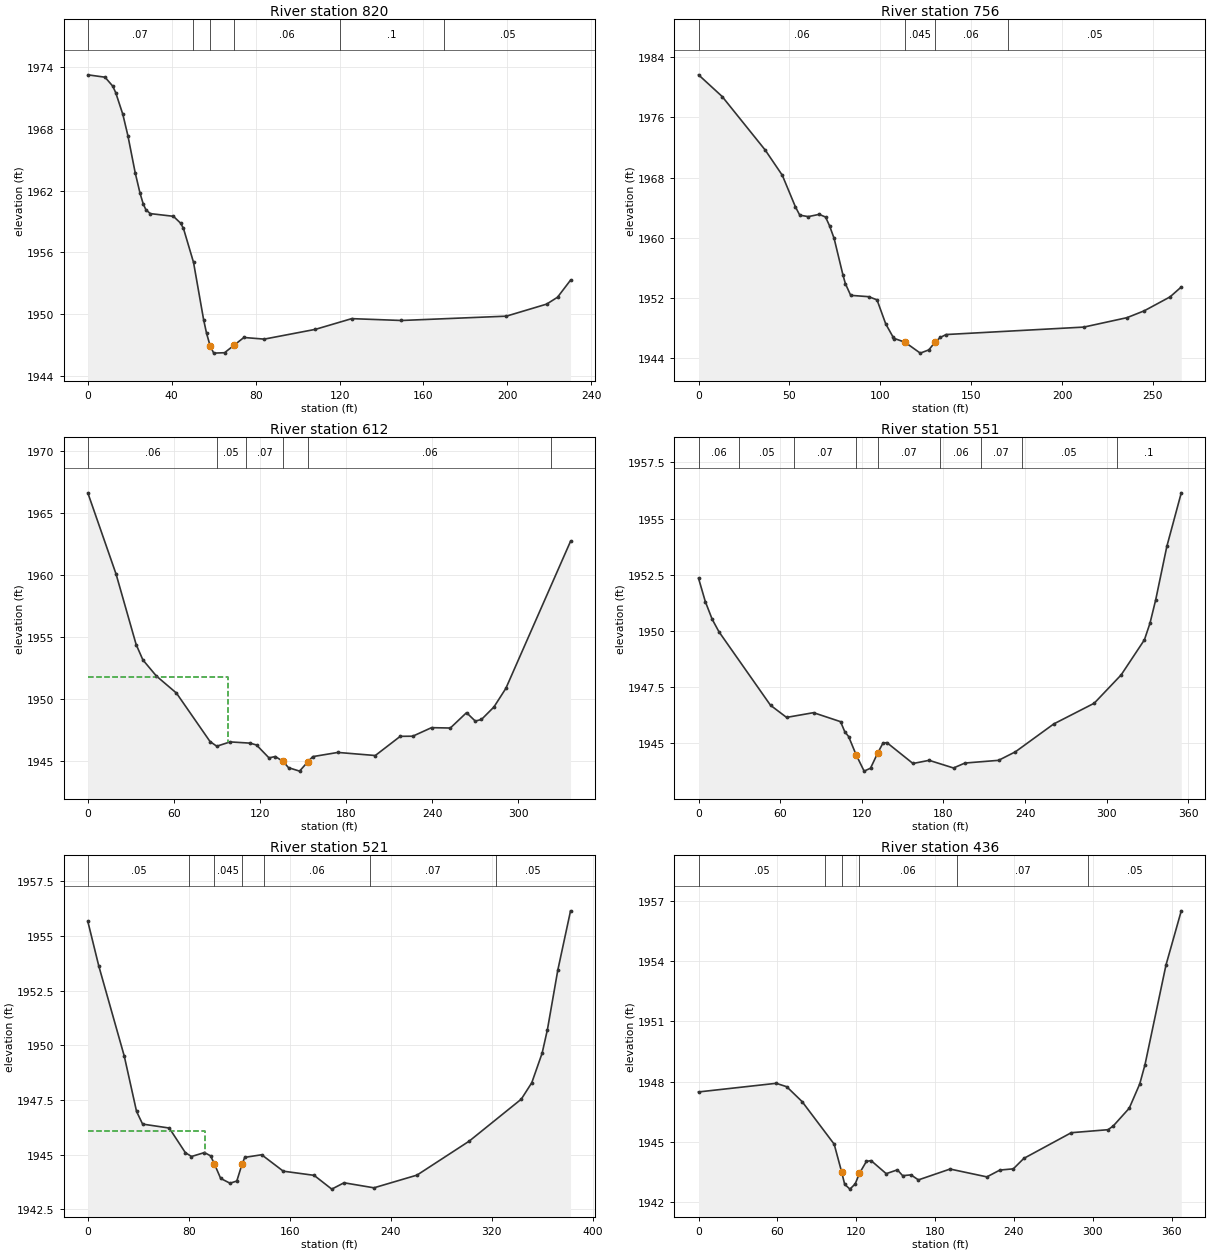
Type RM Length L Ch R = 1 ,820     ,63.7,63.6,65
XS GIS Cut Line= 2
2292140.71566997718947.1073736152292013.02961712718755.714226979
#Sta/Elev= 30
       0 1973.25     8.2 1973.02    11.9 1972.15    13.3 1971.52    16.7 1969.41
    19.1 1967.35    22.6 1963.73    24.9 1961.75    26.4 1960.72    27.7 1960.14
    29.8 1959.77    40.8 1959.51    44.2 1958.85    45.6 1958.33    50.4 1955.03
    55.2 1949.47    56.6 1948.15   58.27 1946.96      60 1946.22    65.2 1946.26
    69.6 1946.97    74.4 1947.74    84.1 1947.58   108.5 1948.53   125.8 1949.57
   149.5 1949.39   199.5 1949.81   218.7 1950.98   223.9 1951.65   230.1 1953.31
#Mann= 6 ,-1,0
       0     .07       0      50     .06       0   58.27    .045       0
    69.6     .06       0     120      .1       0     170     .05       0
Bank Sta=58.27,69.6
XS Rating Curve= 0 ,0
Exp/Cntr(USF)=0,0
Exp/Cntr=0.3,0.1

Type RM Length L Ch R = 1 ,756     ,142,143.8,144.4
XS GIS Cut Line= 2
2292216.74732244718952.1821918982292074.42585616718727.893348184
#Sta/Elev= 30
       0 1981.65      13 1978.77    36.7 1971.65    46.1  1968.3    53.3 1964.11
    55.7    1963    60.4 1962.81    66.4 1963.11    69.9 1962.75    72.1 1961.58
    74.6 1959.91    79.4 1955.11    80.8  1953.9    83.7 1952.35    93.6 1952.17
    98.2 1951.75     103 1948.55   106.9 1946.86   107.8 1946.61  113.58 1946.12
     122 1944.67   126.7  1945.1   130.1 1946.12     133 1946.75   136.2 1947.14
     212 1948.13   235.7 1949.38   245.2 1950.29   259.4 1952.14   265.6 1953.46
#Mann= 4 ,-1,0
       0     .06       0  113.58    .045       0   130.1     .06       0
     170     .05       0
Bank Sta=113.58,130.1
XS Rating Curve= 0 ,0
Exp/Cntr(USF)=0,0
Exp/Cntr=0.3,0.1

Type RM Length L Ch R = 1 ,612     ,52.9,60.7,71.4
XS GIS Cut Line= 3
 2292227.6056735 718902.015429932292286.30746574718805.330125059
2292197.90947272718600.219156866
#Sta/Elev= 30
       0 1966.62    19.7 1960.06    33.7 1954.37    38.4 1953.13    47.8 1951.83
    61.8 1950.45    85.2 1946.54    89.9 1946.16    99.2 1946.51   113.1 1946.41
   117.6 1946.26   126.3 1945.22   130.7 1945.33   136.2 1944.93   139.9 1944.43
   147.6 1944.15  153.49 1944.92   156.8 1945.32   174.3 1945.66   200.4 1945.41
   217.8 1946.96   226.5 1946.97   239.6 1947.66   252.7 1947.63     264 1948.87
   270.1 1948.19   274.4 1948.32   283.1 1949.33   291.4 1950.83   336.5 1962.71
#Mann= 6 ,-1,0
       0     .06       0      90     .05       0     110     .07       0
   136.2    .045       0  153.49     .06       0  323.11      .1       0
#XS Ineff= 2 , 0
           97.54 1951.76
Permanent Ineff=
       F       F
Bank Sta=136.2,153.49
XS Rating Curve= 0 ,0
Exp/Cntr(USF)=0,0
Exp/Cntr=0.3,0.1

Type RM Length L Ch R = 1 ,551     ,29.9,30.7,30.9
XS GIS Cut Line= 4
2292258.32359692718865.2388844312292322.10738327718778.684410937
2292381.52511809718725.2638281882292340.77022386718562.885197757
#Sta/Elev= 30
       0 1952.35       5 1951.31      10 1950.53      15 1949.97    52.9  1946.7
    64.7 1946.16    84.5 1946.37   104.4 1945.97   107.5 1945.52   110.3 1945.31
   115.8  1944.5   121.7 1943.77   126.4  1943.9   131.8 1944.59   135.5 1945.01
   138.4 1945.04   157.6 1944.11   169.5 1944.25   187.4 1943.91   195.8 1944.13
   220.5 1944.25   232.9 1944.63   261.1 1945.87   290.8 1946.79   310.6 1948.05
   327.7 1949.61   331.8 1950.35     336 1951.39   344.2 1953.77   354.8 1956.15
#Mann= 9 ,-1,0
       0     .06       0      30     .05       0      70     .07       0
   115.8    .045       0   131.8     .07       0  177.52     .06       0
  207.42     .07       0  237.42     .05       0  307.42      .1       0
Bank Sta=115.8,131.8
XS Rating Curve= 0 ,0
Exp/Cntr(USF)=0,0
Exp/Cntr=0.3,0.1

Type RM Length L Ch R = 1 ,521     ,95.3,84.3,75.1
XS GIS Cut Line= 5
2292288.01686096718877.1338484232292338.26764137718802.924798086
2292404.26122741718749.8946132822292419.41863362718738.526558623
2292372.32358584718555.447553262
#Sta/Elev= 30
       0 1955.66     8.7 1953.62    28.9  1949.5    38.6 1946.98    43.4  1946.4
    64.5 1946.22    77.2  1945.1    82.1 1944.92    92.4  1945.1    97.2 1944.95
  100.171944.593   105.2 1943.92   112.6  1943.7     118  1943.8   122.11944.561
   124.3 1944.88   137.7    1945   154.8 1944.25   179.2 1944.06   193.2 1943.43
   202.9 1943.72   226.6 1943.49   260.7 1944.07     302 1945.62   343.3 1947.54
   351.6 1948.29   359.8 1949.64     364 1950.72   372.2 1953.43   382.3 1956.14
#Mann= 7 ,-1,0
       0     .05       0      80     .07       0  100.17    .045       0
   122.1     .07       0  139.62     .06       0  223.23     .07       0
  323.23     .05       0
#XS Ineff= 2 , 0
           92.59  1946.1
Permanent Ineff=
       F       F
Bank Sta=100.17,122.1
XS Rating Curve= 0 ,0
Exp/Cntr(USF)=0,0
Exp/Cntr=0.3,0.1

Type RM Length L Ch R = 1 ,436     ,185.9,183.4,181.1
XS GIS Cut Line= 3
2292445.92040129718908.0762173272292441.89276773718861.758431419
2292421.10335536718541.658939534
#Sta/Elev= 30
       0 1947.49    59.1 1947.92    67.1 1947.75    78.8 1947.01   103.2 1944.89
   108.81943.527   111.2 1942.89   115.2 1942.65   119.2 1942.91   122.4 1943.43
   127.7 1944.03   131.3 1944.07   142.8 1943.42   151.3 1943.61   155.3 1943.32
   161.6 1943.36   167.3 1943.11   191.4 1943.65   219.4 1943.26   229.3  1943.6
   239.5 1943.66   247.5 1944.18   283.6 1945.46   311.6 1945.61   315.6  1945.8
   327.7 1946.68   335.7 1947.89   339.7 1948.85   355.7 1953.82   367.3 1956.51
#Mann= 6 ,-1,0
       0     .05       0   96.49     .06       0   108.8    .045       0
   122.4     .06       0  196.49     .07       0  296.49     .05       0
Bank Sta=108.8,122.4
XS Rating Curve= 0 ,0
Exp/Cntr(USF)=0,0
Exp/Cntr=0.3,0.1

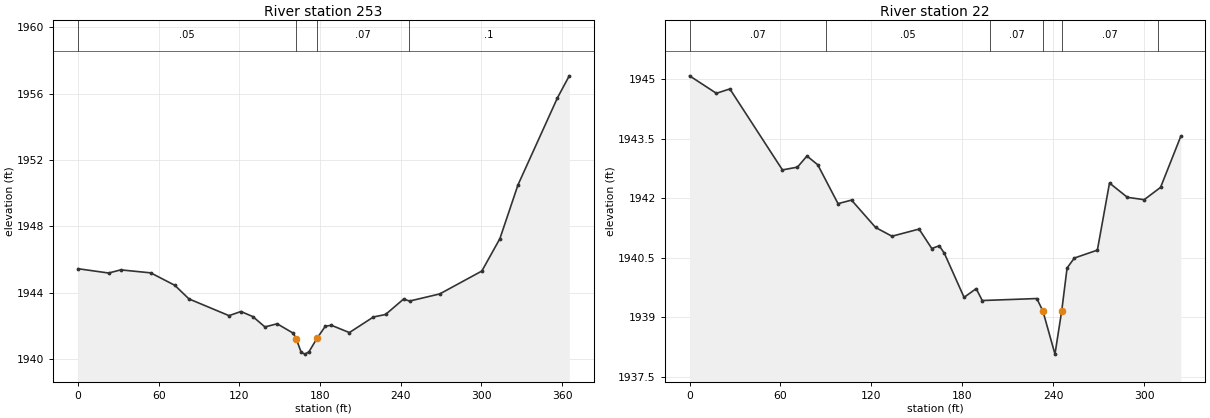
Type RM Length L Ch R = 1 ,253     ,227.5,231.1,232.9
XS GIS Cut Line= 3
2292642.17575532718829.6862293212292617.45023644718779.382587457
2292478.47576824718503.138859252
#Sta/Elev= 30
       0 1945.45    22.8 1945.19    31.8 1945.38    54.1  1945.2      72 1944.45
    82.5 1943.63   112.3 1942.62   121.2 1942.87   130.1 1942.56     139 1941.94
   148.1 1942.13   159.9 1941.57  162.22 1941.24     166  1940.4   168.9  1940.3
   171.8 1940.45   177.8 1941.26   183.9 1941.98   188.4 1942.04   201.8  1941.6
   219.7 1942.54   228.7 1942.69   242.1 1943.62   246.6  1943.5     269 1943.93
   300.3 1945.31   313.7 1947.26   327.2 1950.51   356.5 1955.75   365.3 1957.08
#Mann= 4 ,-1,0
       0     .05       0  162.22    .045       0   177.8     .07       0
  246.05      .1       0
Bank Sta=162.22,177.8
XS Rating Curve= 0 ,0
Exp/Cntr=0.3,0.1

Type RM Length L Ch R = 1 ,22      ,,,
XS GIS Cut Line= 4
2292689.91591235718793.0481843462292764.26043474718642.166963842
2292763.04685458718530.9009241672292730.69139293718499.902361088
#Sta/Elev= 30
       0 1945.08    17.7 1944.64    26.6 1944.75    61.3 1942.71    71.2 1942.78
    77.5 1943.06    84.6 1942.84      98 1941.86   106.9 1941.95   122.8 1941.26
   133.6 1941.04   151.5 1941.22   159.9 1940.73   164.8  1940.8   168.2 1940.61
   181.2  1939.5   189.2 1939.72   193.2 1939.42   229.2 1939.47   233.2 1939.16
   241.2 1938.07  245.66 1939.16   249.2 1940.24     254 1940.49   269.2 1940.69
   277.2 1942.38     289 1942.02   300.1 1941.96   310.9 1942.27   324.3 1943.56
#Mann= 6 ,-1,0
       0     .07       0      90     .05       0   198.2     .07       0
   233.2    .045       0  245.66     .07       0  309.48     .05       0
Bank Sta=233.2,245.66
XS Rating Curve= 0 ,0
Exp/Cntr(USF)=0,0
Exp/Cntr=0.3,0.1
LCMann Table=0

Chan Stop Cuts=-1
Use User Specified Reach Order=0
Composite Channel Slope=5